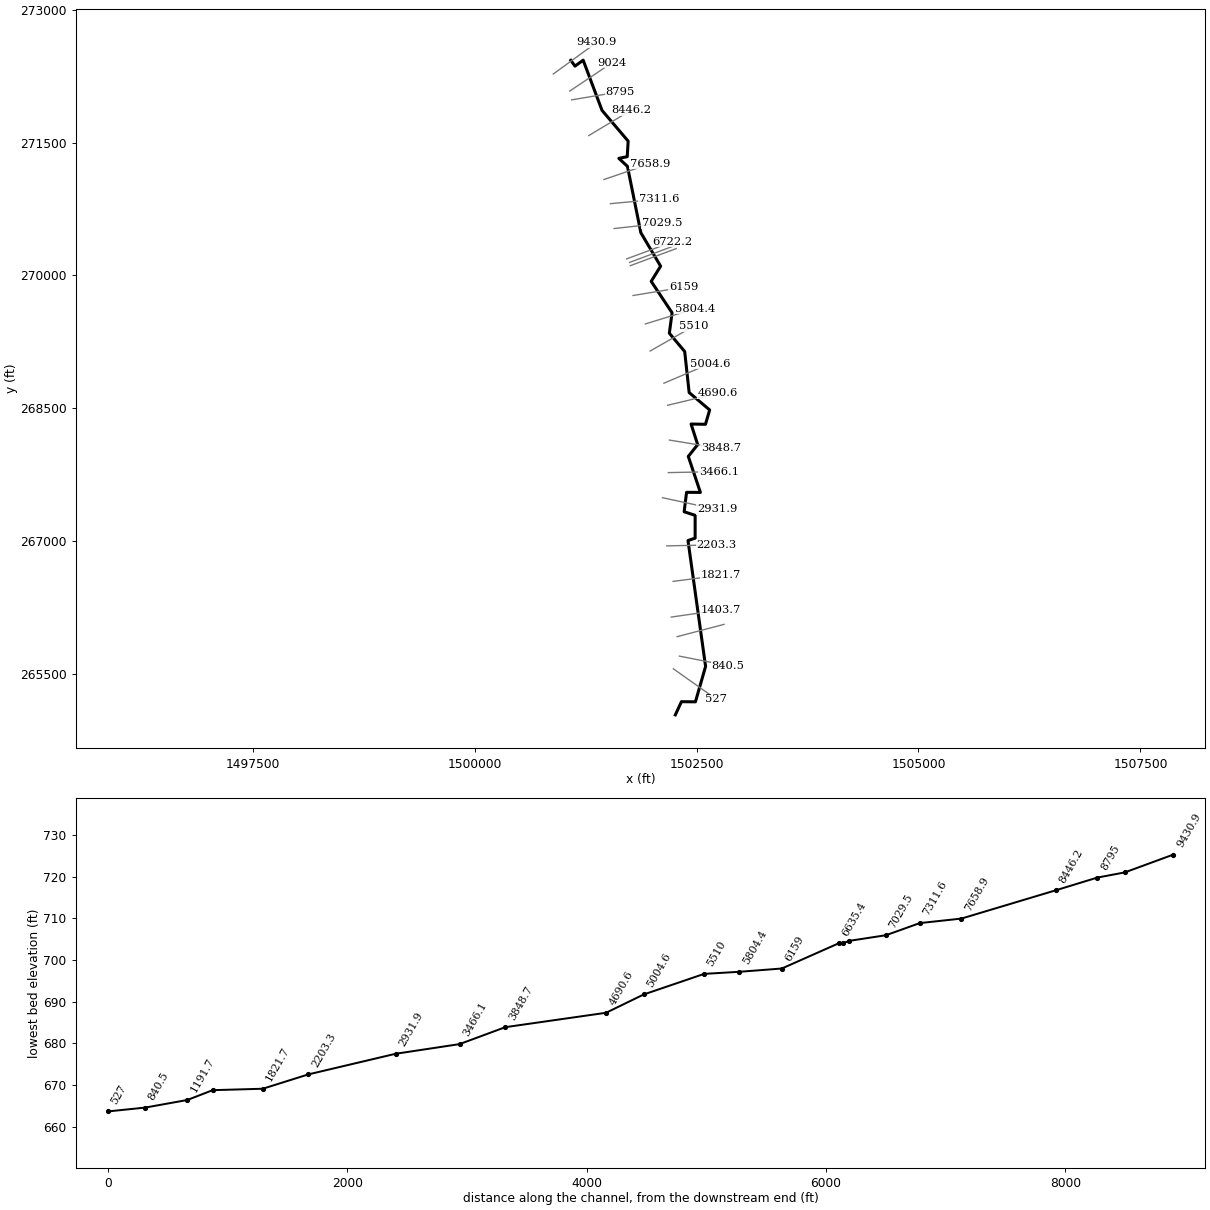
--- BKYRN.prj (project) ---

Proj Title=BKYRN
Current Plan=p01
Default Exp/Contr=0,0
English Units
Geom File=g01
Flow File=f01
Plan File=p01
BEGIN DESCRIPTION:
END DESCRIPTION:
DSS Export Rating Curves= 0
DSS Export Rating Curve Sorted= 0
DSS Export Volume Flow Curves= 0
DXF OffsetX= 0
DXF OffsetY= 0
DXF ScaleX= 0
DXF ScaleY= 0

--- BKYRN.p01 (plan) ---

Plan Title=Floodplain
Program Version=4.00
Geom File=g01
Flow File=f01
K Sum by GR=0
Std Step Tol=0.01
Critical Tol=0.01
Num of Std Step Trials=20
Max Error Tol=0.3
Flow Tol Ratio=0.001
Split Flow NTrial=30
Split Flow Tol=0.02
Split Flow Ratio=0.02
Log Output Level=0
Friction Slope Method=1
Unsteady Friction Slope Method=2
Unsteady Bridges Friction Slope Method=1
Global Log Level=0
CheckData=False
Run HTab=0
Run UNet=0
Run PostProcess=0
UNET Theta=0
UNET Theta Warmup=0
UNET ZTol=0
UNET ZSATol=0
UNET MxIter=0
UNET MaxInSteps=0
UNET DtIC=0
UNET DtMin=0
UNET MaxCRTS=0
UNET WFStab=0
UNET SFStab=0
UNET WFX=0
UNET SFX=0
UNET DSS MLevel=0
UNET DZMax Abort=0
UNET Convert EG Bridges=0
UNET Use Existing IB Tables=0
UNET Froude Limit=0
UNET Froude Power=0
Write IC File=0
Echo Input=False
Echo Output=False
Write Detailed=0

--- BKYRN.f01 (steady flow) ---

Flow Title=NFF Regression Equation
Program Version=4.10
Number of Profiles= 1
Profile Names=P100yr
River Rch & RM=BKYRN,Main            ,9430.9
950.7046
River Rch & RM=BKYRN,Main            ,7658.9
982.2056
River Rch & RM=BKYRN,Main            ,6159
1088.088
River Rch & RM=BKYRN,Main            ,840.5
1189.966
River Rch & RM=BKYRN,Main            ,527
1191.501
Boundary for River Rch & Prof#=BKYRN,Main            , 1
Up Type= 0
Dn Type= 3
Dn Slope=0.004
DSS Import GetInterval= 0
DSS Import GetPeak= 0
DSS Import FillOption= 0

--- BKYRN.g01 (geometry) ---

Geom Title=USGS 10m DEM
Program Version=4.10

River Reach=BKYRN           ,Main
Reach XY= 30
     1501083.763      272427.244     1501131.167      272362.045
     1501223.113      272429.036     1501435.493      271862.393
     1501729.793      271515.622     1501719.271      271340.156
     1501624.743      271321.091     1501721.809      271231.006
     1501872.705      270481.984     1502095.279      270104.349
     1501989.395       269933.04     1502224.519      269578.442
     1502193.649      269347.926     1502366.551      269141.217
     1502416.916      268678.009     1502647.919      268481.842
     1502600.593      268320.022     1502438.472      268322.895
     1502512.898      268090.517     1502407.096      267957.768
     1502543.391      267551.234     1502387.557      267552.327
     1502360.407      267332.979     1502484.356      267292.542
     1502484.163      267035.102     1502403.781      267008.026
     1502601.919      265587.747     1502487.547      265188.023
     1502330.169      265189.716     1502261.061      265041.032

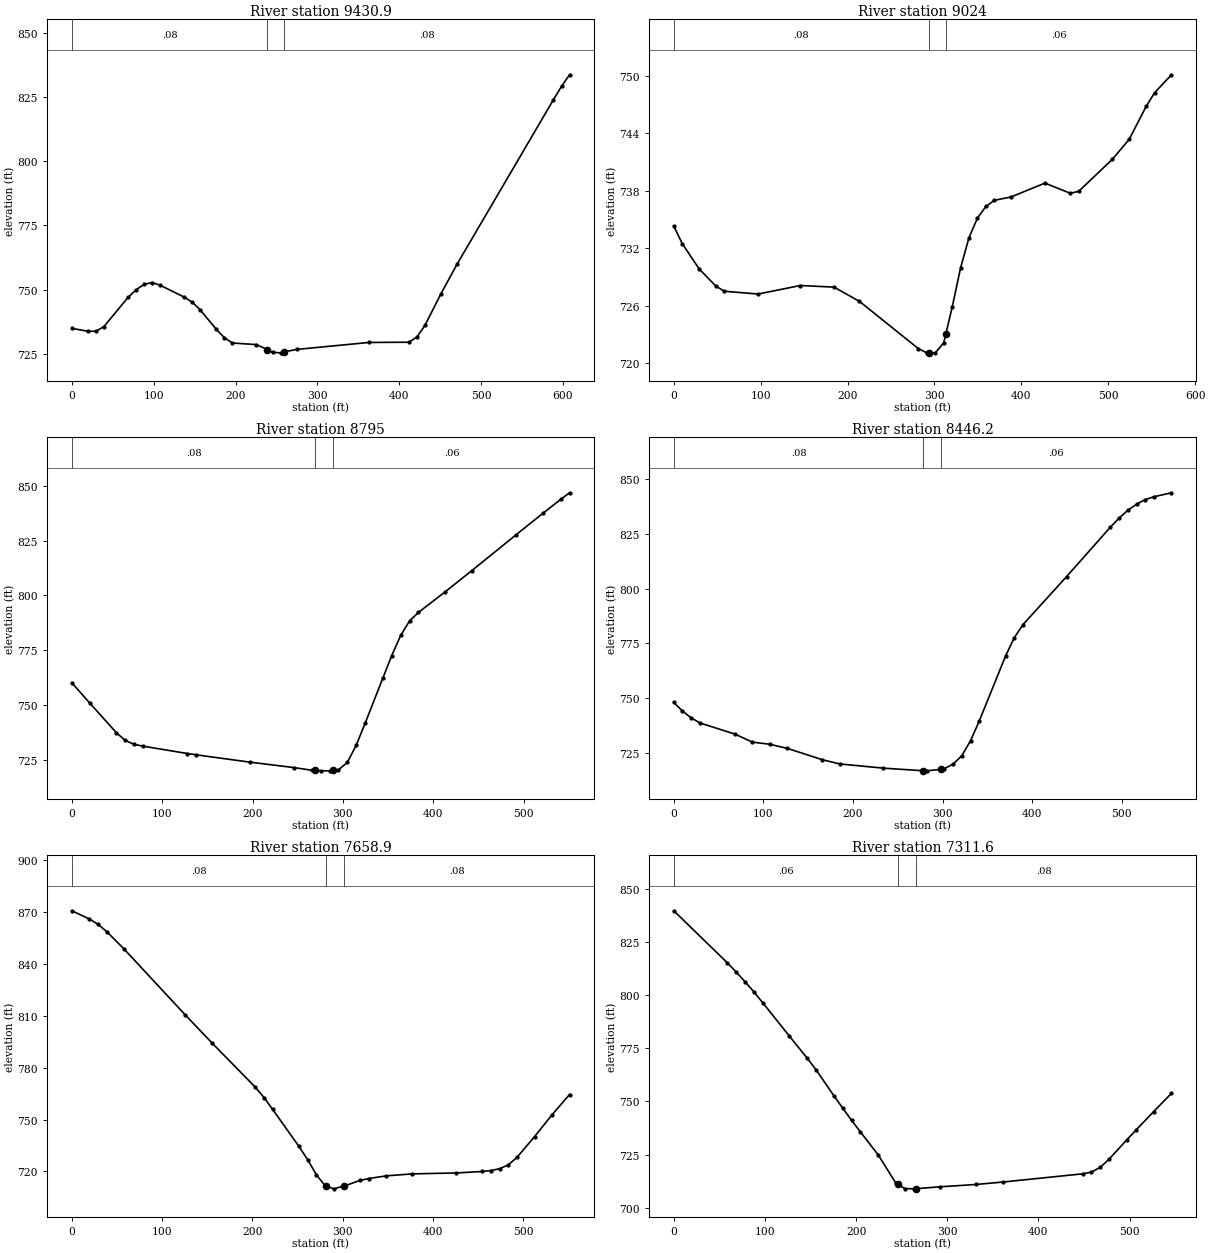
Type RM Length L Ch R = 1 ,9430.9  ,407.6,406.9,385.5
XS GIS Cut Line= 2
     1500886.287       272273.08     1501377.992      272631.047
#Sta/Elev= 30
       0  734.88    19.6  733.76    29.4  733.75    39.2  735.58    68.7  746.98
    78.5  749.92    88.3  752.03    98.1  752.76   107.9  751.69   137.3  747.07
   147.2  745.08     157  742.03   176.6  734.48   186.4  731.25   196.2  729.18
   225.6  728.56   238.9726.6292   245.2  725.55     255  725.35   258.9725.6935
   274.7  726.68     363  729.39     412  729.49   421.8  731.56   431.6  736.11
   451.2  748.46   470.9  759.99   588.6  824.04   598.4   829.2   608.2  833.71
#Mann= 3 , 0 , 0
       0     .08       0   238.9    .045       0   258.9     .08       0
Bank Sta=238.9,258.9
XS Rating Curve= 0 ,0
Exp/Cntr=0.3,0.1

Type RM Length L Ch R = 1 ,9024    ,238.5,229.1,219.3
XS GIS Cut Line= 2
     1501071.881      272080.926     1501548.015      272399.315
#Sta/Elev= 30
       0  734.28     9.7  732.47    29.1  729.83    48.5  728.02    58.2  727.49
    97.1   727.2   145.6  728.09   184.4  727.92   213.6  726.44   281.5   721.5
   291.2  721.06   293.2  721.06     301  721.06   310.7  722.11   313.2723.0662
   320.4  725.82   330.1  729.94   339.8   733.1   349.5  735.13   359.2  736.34
   368.9  736.98   388.3  737.34   427.2  738.78   456.3  737.72     466  737.92
   504.8  741.27   524.2  743.36   543.6  746.78   553.4  748.22   572.8  750.09
#Mann= 3 , 0 , 0
       0     .08       0   293.2    .045       0   313.2     .06       0
Bank Sta=293.2,313.2
XS Rating Curve= 0 ,0
Exp/Cntr=0.3,0.1

Type RM Length L Ch R = 1 ,8795    ,339.7,348.8,356.4
XS GIS Cut Line= 2
     1501092.997      271981.294     1501636.183      272072.247
#Sta/Elev= 30
       0  760.07    19.7  750.84    49.2   737.3      59  733.74    68.8  731.93
    78.7   731.1   127.8  727.74   137.7  727.14   196.7  723.81   245.9  721.31
   265.5  720.08   269.3719.9895   275.4  719.84   285.2  719.82   289.3719.9967
     295  720.24   304.9  723.68   314.7  731.53   324.6  741.59   344.2  762.23
     354  772.45   363.9  781.72   373.7   788.3   383.6  792.24   413.1  801.62
   442.6  811.32   491.7  827.75   521.2  837.48   540.9  843.86   550.8  846.92
#Mann= 3 , 0 , 0
       0     .08       0   269.3    .045       0   289.3     .06       0
Bank Sta=269.3,289.3
XS Rating Curve= 0 ,0
Exp/Cntr=0.3,0.1

Type RM Length L Ch R = 1 ,8446.2  ,706.2,787.2,780
XS GIS Cut Line= 2
     1501285.783      271578.211     1501762.307      271863.622
#Sta/Elev= 30
       0     748     9.7  744.06    19.5  740.94    29.2  738.63    68.2  733.54
    87.7  729.88   107.2  728.88   126.7  727.02   165.7  721.85   185.2   719.9
   233.9  717.98   278.2716.8021   282.6  716.75   298.2717.4526   302.1   717.8
   311.8   719.8   321.6  723.73   331.3  730.57   341.1  739.66   370.3  769.23
     380  777.58   389.8  783.59   438.5  805.55   487.2  828.05     497  832.22
   506.7  835.77   516.5  838.57   526.2   840.7     536  842.01   555.5  843.81
#Mann= 3 , 0 , 0
       0     .08       0   278.2    .045       0   298.2     .06       0
Bank Sta=278.2,298.2
XS Rating Curve= 0 ,0
Exp/Cntr=0.3,0.1

Type RM Length L Ch R = 1 ,7658.9  ,352.7,347.4,342.1
XS GIS Cut Line= 2
     1501456.693      271082.155     1501978.331        271260.3
#Sta/Elev= 30
       0  870.55    19.3  865.84      29  862.72    38.7  858.48      58  848.37
   125.7  810.36   154.7  794.48   203.1  768.71   212.8  762.69   222.4  755.84
   251.4  734.54   261.1  726.85   270.8  718.15   280.4  711.74   281.5711.5383
   290.1  709.97   301.5711.5775   319.1  714.83   328.8  715.93   348.1  717.46
   377.2  718.61   425.5  719.14   454.5  719.99   464.2  720.55   473.8  721.62
   483.5  723.82   493.2  728.28   512.5  740.16   531.9  752.79   551.2  764.44
#Mann= 3 , 0 , 0
       0     .08       0   281.5    .045       0   301.5     .08       0
Bank Sta=281.5,301.5
XS Rating Curve= 0 ,0
Exp/Cntr=0.3,0.1

Type RM Length L Ch R = 1 ,7311.6  ,281.9,282.1,282.4
XS GIS Cut Line= 2
     1501530.018      270809.836     1502073.665      270860.467
#Sta/Elev= 30
       0  839.66    58.5  815.29    68.2  810.97      78  806.39    87.8  801.56
    97.5  796.46   126.8  780.72   146.2  770.41     156  764.92   175.5  752.75
   185.2   746.9     195  741.16   204.8  735.61   224.2  724.91   243.8  711.43
   245.5711.0091   253.5  709.02     263  708.89   265.5708.9575   292.5  709.86
   331.5  710.94   360.8  712.08   448.5  715.95   458.2  716.77     468  719.04
   477.8  722.95   497.2  732.04     507  736.49   526.5  745.22     546  753.82
#Mann= 3 , 0 , 0
       0     .06       0   245.5    .045       0   265.5     .08       0
Bank Sta=245.5,265.5
XS Rating Curve= 0 ,0
Exp/Cntr=0.3,0.1

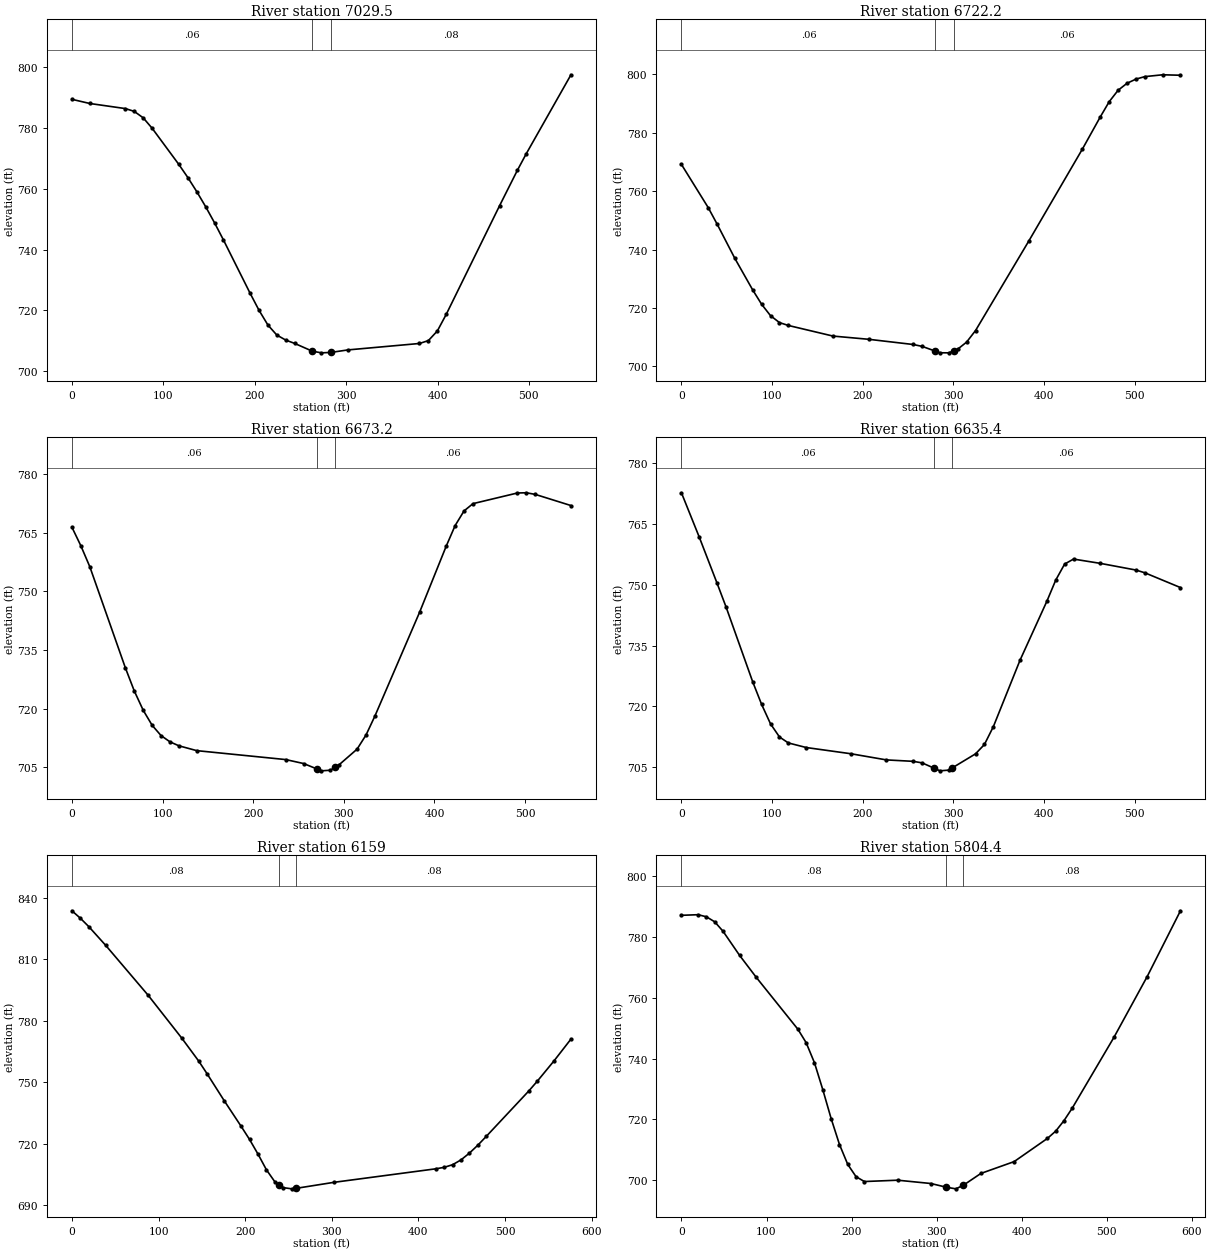
Type RM Length L Ch R = 1 ,7029.5  ,301.5,307.3,312.9
XS GIS Cut Line= 2
     1501571.668      270529.194     1502114.405      270588.801
#Sta/Elev= 30
       0  789.44    19.5  788.07    58.5  786.39    68.2  785.47      78  783.34
    87.8   779.9     117  767.99   126.8   763.7   136.5  759.09   146.2  754.15
     156  748.81   165.8  743.13     195  725.56   204.8  719.93   214.5   715.1
   224.2  711.83     234  710.17   243.8  709.07     263706.5254     273  705.98
     283706.1086   302.2  706.95   380.2  709.06     390  710.01   399.8  713.18
   409.5  718.63     468  754.48   487.5  766.15   497.2  771.59     546  797.52
#Mann= 3 , 0 , 0
       0     .06       0     263    .045       0     283     .08       0
Bank Sta=263,283
XS Rating Curve= 0 ,0
Exp/Cntr=0.3,0.1

Type RM Length L Ch R = 1 ,6722.2  ,49,49,49
XS GIS Cut Line= 2
     1501713.007      270186.543     1502228.936      270378.955
#Sta/Elev= 30
       0  769.13    29.5  754.37    39.3  748.74      59  736.92    78.7  726.12
    88.5  721.24    98.3  717.34   108.2  714.97     118  713.99   167.2  710.36
   206.5  709.26   255.6  707.48   265.5  706.84   280.2 705.197   285.2  704.64
     295  704.62   300.2705.2904   304.8  705.88   314.6  708.28   324.5  712.25
   383.5  743.03   442.5  774.44   462.2  785.43     472  790.62   481.8  794.52
   491.6   796.9   501.5  798.34   511.3  799.19     531  799.82   550.6  799.66
#Mann= 3 , 0 , 0
       0     .06       0   280.2    .045       0   300.2     .06       0
Bank Sta=280.2,300.2
XS Rating Curve= 0 ,0
Exp/Cntr=0.3,0.1

Type RM Length L Ch R = 1 ,6673.2  ,37.9,37.8,37.9
XS GIS Cut Line= 2
      1501745.76      270146.922     1502261.689      270339.334
#Sta/Elev= 30
       0  766.43     9.8  761.71    19.7  756.34      59  730.42    68.8  724.52
    78.7  719.56    88.5  715.74    98.3  713.11   108.2   711.5     118  710.49
   137.7  709.25     236  706.96   255.6  705.95     270704.5928   275.3  704.08
   285.2  704.24     290704.9467     295  705.68   314.6  709.63   324.5  713.26
   334.3  718.11   383.5  744.62     413  761.61   422.8  766.86   432.6   770.6
   442.5  772.47   491.6   775.2   501.5  775.25   511.3  774.83   550.6  771.98
#Mann= 3 , 0 , 0
       0     .06       0     270    .045       0     290     .06       0
Bank Sta=270,290
XS Rating Curve= 0 ,0
Exp/Cntr=0.3,0.1

Type RM Length L Ch R = 1 ,6635.4  ,481,476.4,471.1
XS GIS Cut Line= 2
     1501754.673      270110.154     1502270.603      270302.566
#Sta/Elev= 30
       0  772.75    19.7  761.78    39.3  750.42    49.2  744.56    78.7  726.01
    88.5  720.45    98.3  715.66   108.2  712.41     118  710.94   137.7  709.81
   186.8  708.28   226.2  706.75   255.6   706.4   265.5  706.02   278.8704.7084
   285.2  704.05     295  704.23   298.8704.7759   324.5  708.25   334.3  710.56
   344.2  714.99   373.6  731.39   403.2  745.95     413  751.18   422.8  755.14
   432.6  756.37   462.2  755.31   501.5  753.66   511.3  752.98   550.6  749.33
#Mann= 3 , 0 , 0
       0     .06       0   278.8    .045       0   298.8     .06       0
Bank Sta=278.8,298.8
XS Rating Curve= 0 ,0
Exp/Cntr=0.3,0.1

Type RM Length L Ch R = 1 ,6159    ,351.5,354.7,357.7
XS GIS Cut Line= 2
     1501784.957      269773.415     1502353.473      269866.438
#Sta/Elev= 30
       0  833.66     9.8     830    19.5  825.91    39.1  816.73    87.9  792.48
   126.9  771.47   146.5  760.24   156.2  754.02   175.8  740.98   195.3  728.51
     205  722.11   214.8  714.93   224.6  707.23   234.3  701.39   239.2 699.973
   244.1  698.56   253.9  697.98   259.2698.2504   302.7  701.17   419.8  707.74
   429.6  708.46   439.4  709.74   449.1  712.09   458.9  715.42   468.7  719.32
   478.4  723.61   527.3  745.68     537  750.39   556.6  760.45   576.1  771.06
#Mann= 3 , 0 , 0
       0     .08       0   239.2    .045       0   259.2     .08       0
Bank Sta=239.2,259.2
XS Rating Curve= 0 ,0
Exp/Cntr=0.3,0.1

Type RM Length L Ch R = 1 ,5804.4  ,289.8,294.3,297
XS GIS Cut Line= 2
     1501923.652      269452.468     1502484.193      269625.352
#Sta/Elev= 30
       0  787.08    19.6  787.28    29.3   786.6    39.1  784.95    48.9  781.84
    68.4   773.9      88  766.68   136.9  749.64   146.6  745.22   156.4  738.61
   166.2  729.76     176  720.26   185.8  711.75   195.5  705.22   205.3  701.17
   215.1  699.59   254.2  700.03   293.3  698.94   311.3 697.726   322.6  697.19
   331.3698.3533     352  702.25   391.1  706.14   430.2  713.76     440  716.17
   449.7  719.61   459.5  723.76   508.4  746.97   547.5  766.96   586.6  788.57
#Mann= 3 , 0 , 0
       0     .08       0   311.3    .045       0   331.3     .08       0
Bank Sta=311.3,331.3
XS Rating Curve= 0 ,0
Exp/Cntr=0.3,0.1

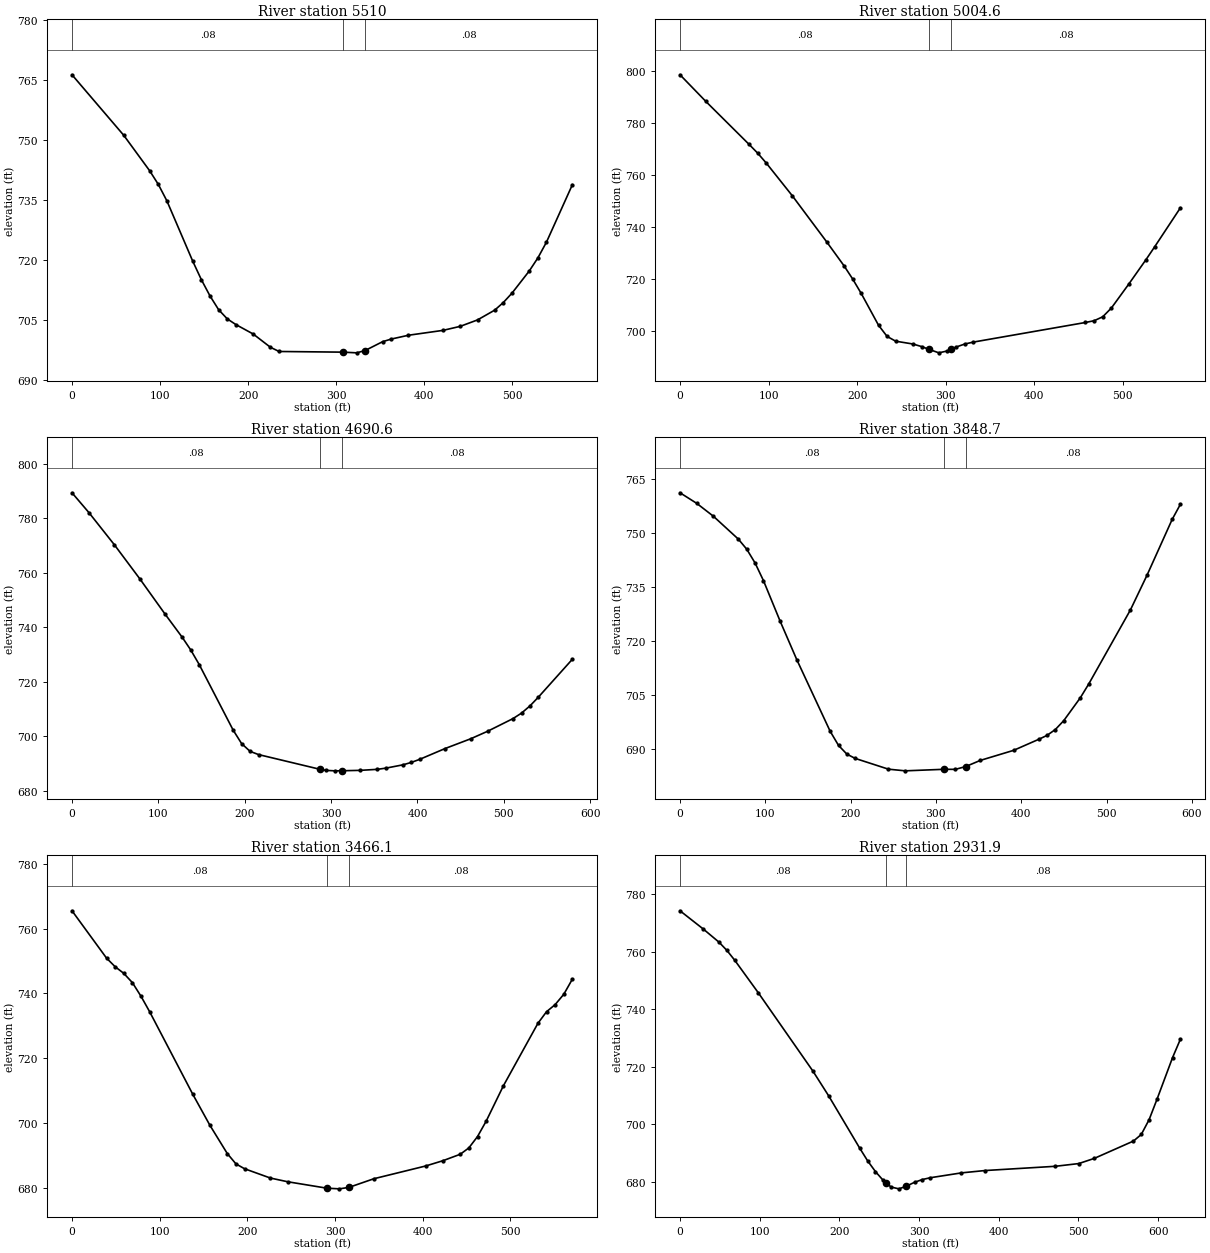
Type RM Length L Ch R = 1 ,5510    ,507.1,505.5,502.6
XS GIS Cut Line= 2
     1501977.298      269146.911     1502470.512      269428.803
#Sta/Elev= 30
       0  766.37    58.8  751.19    88.2  742.31      98   738.9   107.7  734.79
   137.1  719.65   146.9  715.01   156.7  710.94   166.5  707.49   176.3   705.2
   186.1  703.77   205.7  701.41   225.3  698.08   235.1  697.03   307.7696.8624
   323.2  696.69   332.7697.2619   352.6  699.48   362.4  700.14     382   701.1
   421.2  702.32   440.8  703.33   460.4  704.94   479.9  707.39   489.7   709.3
   499.5  711.64   519.1  717.19   528.9  720.47   538.7  724.44   568.1  738.83
#Mann= 3 , 0 , 0
       0     .08       0   307.7    .045       0   332.7     .08       0
Bank Sta=307.7,332.7
XS Rating Curve= 0 ,0
Exp/Cntr=0.3,0.1

Type RM Length L Ch R = 1 ,5004.6  ,318.3,314,309.7
XS GIS Cut Line= 2
     1502132.435       268783.46     1502652.194      269005.635
#Sta/Elev= 30
       0  798.43    29.2   788.2      78  771.73    87.7  768.37    97.5  764.53
   126.7  752.07   165.7  734.31   185.2  725.17   194.9  720.14   204.7  714.52
   224.2  702.35   233.9  698.04   243.6  696.21   263.1  695.13   272.9  694.14
   281.2 693.079   292.4  691.74   302.1  692.48   306.2693.1034   311.9  693.97
   321.6  695.12   331.4  695.87     458  703.39   467.8  704.07   477.5  705.58
   487.3  708.96   506.8  718.08   526.3  727.48     536  732.36   565.2  747.38
#Mann= 3 , 0 , 0
       0     .08       0   281.2    .045       0   306.2     .08       0
Bank Sta=281.2,306.2
XS Rating Curve= 0 ,0
Exp/Cntr=0.3,0.1

Type RM Length L Ch R = 1 ,4690.6  ,846.1,841.9,832.3
XS GIS Cut Line= 2
     1502174.144      268534.756     1502737.615      268669.659
#Sta/Elev= 30
       0  789.42    19.6  782.14    49.1  770.32    78.6   757.8     108  744.78
   127.7  736.34   137.5  731.72   147.3  726.37   186.6   702.3   196.4  697.35
   206.2   694.5     216  693.32   287.2687.9103   294.6  687.51   304.4  687.35
   312.2687.3743   333.9  687.53   353.5   687.9   363.4  688.34     383  689.54
   392.8  690.43   402.6  691.57   432.1  695.55   461.6  699.11   481.2  701.87
   510.6  706.52   520.5  708.54   530.3  711.19   540.1  714.43   579.4  728.32
#Mann= 3 , 0 , 0
       0     .08       0   287.2    .045       0   312.2     .08       0
Bank Sta=287.2,312.2
XS Rating Curve= 0 ,0
Exp/Cntr=0.3,0.1

Type RM Length L Ch R = 1 ,3848.7  ,378.3,382.6,386.6
XS GIS Cut Line= 2
      1502194.62      268141.877     1502773.581      268047.208
#Sta/Elev= 30
       0  761.21    19.6  758.27    39.1  754.69    68.4  748.32    78.2  745.53
      88  741.69    97.8   736.8   117.3  725.55   136.9   714.8     176   694.9
   185.8  690.97   195.6  688.54   205.3  687.35   244.4  684.35     264  683.89
   309.8684.3226   322.7   684.3   334.8685.0698     352  686.79   391.1  689.59
   420.4  692.64   430.2  693.74     440  695.38   449.8  697.83   469.3  704.21
   479.1  708.02     528  728.63   547.5   738.3   576.9  753.78   586.6  758.01
#Mann= 3 , 0 , 0
       0     .08       0   309.8    .045       0   334.8     .08       0
Bank Sta=309.8,334.8
XS Rating Curve= 0 ,0
Exp/Cntr=0.3,0.1

Type RM Length L Ch R = 1 ,3466.1  ,538.3,534.2,528.4
XS GIS Cut Line= 2
     1502181.775      267774.679     1502752.388      267786.323
#Sta/Elev= 30
       0  765.46    39.4  750.88    49.2  748.23      59   746.2    68.9  743.32
    78.7  739.13    88.6  734.35   137.8  708.92   157.4  699.34   177.1  690.69
     187   687.5   196.8  686.01   226.3  683.14     246     682   290.8680.0172
     305  679.82   315.8680.2664   344.4  682.94   403.4  686.86   423.1  688.49
   442.8  690.47   452.6  692.42   462.5  695.92   472.3  700.63     492  711.55
   531.4   730.8   541.2  734.37     551  736.55   560.9  739.74   570.7  744.41
#Mann= 3 , 0 , 0
       0     .08       0   290.8    .045       0   315.8     .08       0
Bank Sta=290.8,315.8
XS Rating Curve= 0 ,0
Exp/Cntr=0.3,0.1

Type RM Length L Ch R = 1 ,2931.9  ,712.4,728.6,685.3
XS GIS Cut Line= 2
     1502116.731      267491.663     1502730.454      267359.045
#Sta/Elev= 30
       0  774.33    29.4  767.93      49  763.38    58.9  760.51    68.7  757.09
    98.1  745.83   166.8  718.49   186.4  709.94   225.6  691.62   235.5  687.22
   245.3  683.49   255.1  680.41   258.8679.5466   264.9  678.12   274.7   677.5
   283.8678.4012   294.3  679.78   304.1  680.74   313.9  681.36   353.2  683.06
   382.6  683.87   470.9  685.35   500.4   686.3     520  688.12     569  694.14
   578.8  696.43   588.6  701.56   598.5  708.66   618.1  723.23   627.9   729.6
#Mann= 3 , 0 , 0
       0     .08       0   258.8    .045       0   283.8     .08       0
Bank Sta=258.8,283.8
XS Rating Curve= 0 ,0
Exp/Cntr=0.3,0.1

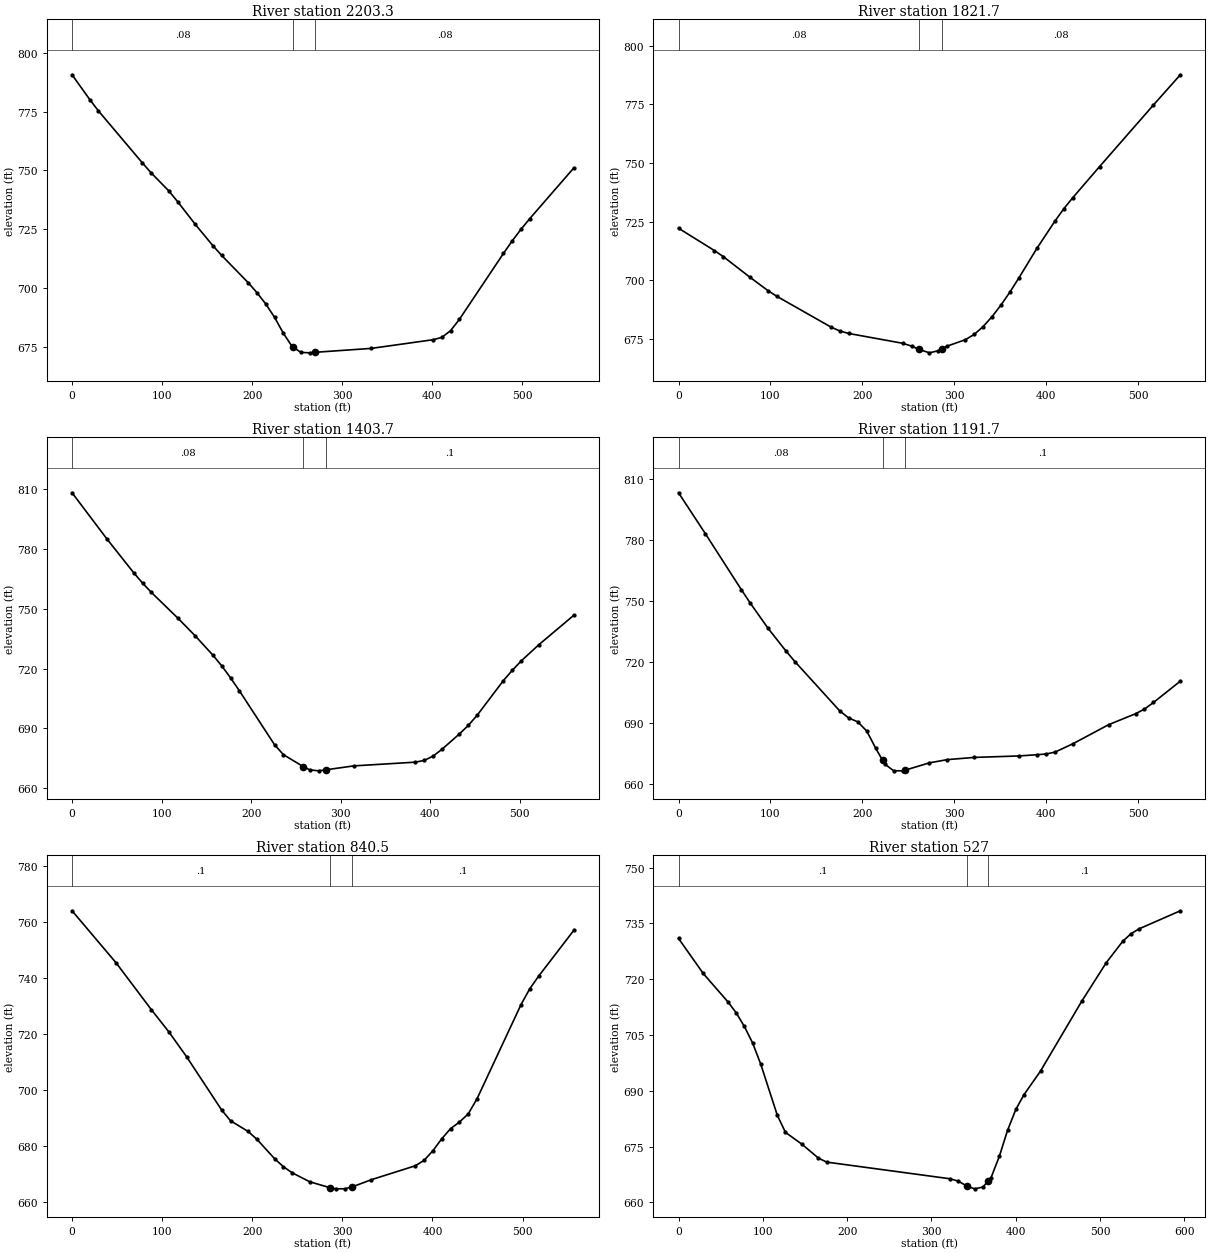
Type RM Length L Ch R = 1 ,2203.3  ,379.1,381.6,384.2
XS GIS Cut Line= 2
     1502164.611      266947.922     1502721.772       266959.57
#Sta/Elev= 30
       0   790.6    19.6   780.1    29.3  775.26    78.2  753.14      88  748.88
   107.6  741.23   117.3  736.72   136.9  727.06   156.4  718.05   166.2  713.88
   195.5  702.39   205.3  698.11   215.1  693.31   224.9  687.62   234.6   680.9
   244.4  675.22   245.2675.0172   254.2  672.74     264  672.55   270.2 672.786
   332.4  674.44   400.8  678.11   410.6   679.1   420.4  681.97   430.2  686.78
   479.1  714.75   488.8  720.06   498.6  725.01   508.4  729.56   557.3  751.07
#Mann= 3 , 0 , 0
       0     .08       0   245.2    .045       0   270.2     .08       0
Bank Sta=245.2,270.2
XS Rating Curve= 0 ,0
Exp/Cntr=0.3,0.1

Type RM Length L Ch R = 1 ,1821.7  ,417.5,418,418.5
XS GIS Cut Line= 2
     1502235.867      266547.278     1502777.411      266616.892
#Sta/Elev= 30
       0  722.23      39  712.73    48.8   710.1      78  701.25    97.5  695.58
   107.2  693.14   165.8  680.11   175.5  678.42   185.2  677.36   243.8  673.18
   253.5  671.99   261.5670.5962     273   669.1   282.8  670.02   286.5670.7753
   292.5     672     312  674.68   321.8  676.97   331.5  680.33   341.2  684.56
     351  689.56   360.8  695.14   370.5  701.15     390   713.7   409.5  725.24
   419.2  730.53     429  735.27   458.2  748.55   516.8  774.81     546  787.67
#Mann= 3 , 0 , 0
       0     .08       0   261.5    .045       0   286.5     .08       0
Bank Sta=261.5,286.5
XS Rating Curve= 0 ,0
Exp/Cntr=0.3,0.1

Type RM Length L Ch R = 1 ,1403.7  ,209.3,212,214.3
XS GIS Cut Line= 2
     1502215.196      266144.487     1502769.933      266224.684
#Sta/Elev= 30
       0  808.03    39.3  784.69    68.8  768.01    78.7  762.82    88.5  758.16
     118  745.32   137.7   736.3   157.3   726.7   167.2  721.33     177  715.36
   186.8  708.91   226.2  681.82     236  676.89   258.1670.9216   265.5  669.26
   275.3  668.76   283.1669.2499   314.7  671.24   383.5  673.11   393.3  673.98
   403.2  676.12     413  679.48   432.7  687.26   442.5  691.47   452.3  696.49
   481.8  713.97   491.7  719.08   501.5  723.72   521.2  731.86   560.5   746.7
#Mann= 3 , 0 , 0
       0     .08       0   258.1    .045       0   283.1      .1       0
Bank Sta=258.1,283.1
XS Rating Curve= 0 ,0
Exp/Cntr=0.3,0.1

Type RM Length L Ch R = 1 ,1191.7  ,361.8,351.2,340.1
XS GIS Cut Line= 2
     1502281.385      265923.372     1502809.577      266062.138
#Sta/Elev= 30
       0  803.37    29.3  783.15    68.3  755.68      78  749.07    97.5  736.56
     117  725.37   126.8  720.14   175.5   695.9   185.3   692.4     195  690.55
   204.8  686.02   214.6  677.53     222671.6405   224.3  669.81     234  666.46
   243.8   666.4     247666.7918   273.1  670.34   292.6  671.93   321.8  673.01
   370.6  673.74   390.1  674.34   399.8  674.68   409.6  675.61   429.1  679.71
   468.1  689.14   497.4  694.53   507.1  696.83   516.9  700.08   546.1  710.58
#Mann= 3 , 0 , 0
       0     .08       0     222    .045       0     247      .1       0
Bank Sta=222,247
XS Rating Curve= 0 ,0
Exp/Cntr=0.3,0.1

Type RM Length L Ch R = 1 ,840.5   ,322.7,313.5,304.1
XS GIS Cut Line= 2
     1502307.229      265703.777     1502853.646      265596.213
#Sta/Elev= 30
       0  763.95    48.8  745.37    87.9  728.65   107.5  720.64     127  711.84
   166.1  692.71   175.9  688.91   195.4  685.08   205.2  682.27   224.7  675.37
   234.5  672.49   244.3  670.31   263.8   667.1     286665.0087   293.1  664.58
   302.9  664.61     311665.2943   332.2  667.85     381  672.83   390.8  674.79
   400.6  678.26   410.4  682.52   420.1  686.11   429.9  688.44   439.7  691.37
   449.4  696.74   498.3  730.45     508   736.1   517.8  740.58   556.9  756.99
#Mann= 3 , 0 , 0
       0      .1       0     286    .045       0     311      .1       0
Bank Sta=286,311
XS Rating Curve= 0 ,0
Exp/Cntr=0.3,0.1

Type RM Length L Ch R = 1 ,527     ,532.7,527,517.8
XS GIS Cut Line= 2
      1502238.39      265561.124     1502723.835      265216.896
#Sta/Elev= 30
       0  730.97    29.3  721.55    58.5  713.94    68.3  711.01      78  707.34
    87.8   702.9    97.6  697.11   117.1  683.45   126.8  678.84   146.3  675.65
   165.8  671.93   175.6  670.84   321.9  666.36   331.7  665.73   342.4  664.35
   351.2  663.65     361  664.13   367.4665.8193   370.7  666.69   380.5  672.42
   390.2  679.38     400     685   409.7  688.97   429.3  695.32     478  714.02
   507.3  724.47   526.8   730.2   536.6  732.24   546.3  733.56   595.1  738.41
#Mann= 3 , 0 , 0
       0      .1       0   342.4    .045       0   367.4      .1       0
Bank Sta=342.4,367.4
XS Rating Curve= 0 ,0
Exp/Cntr=0.3,0.1

Chan Stop Cuts=-1
Use User Specified Reach Order=0
Composite Channel Slope=5